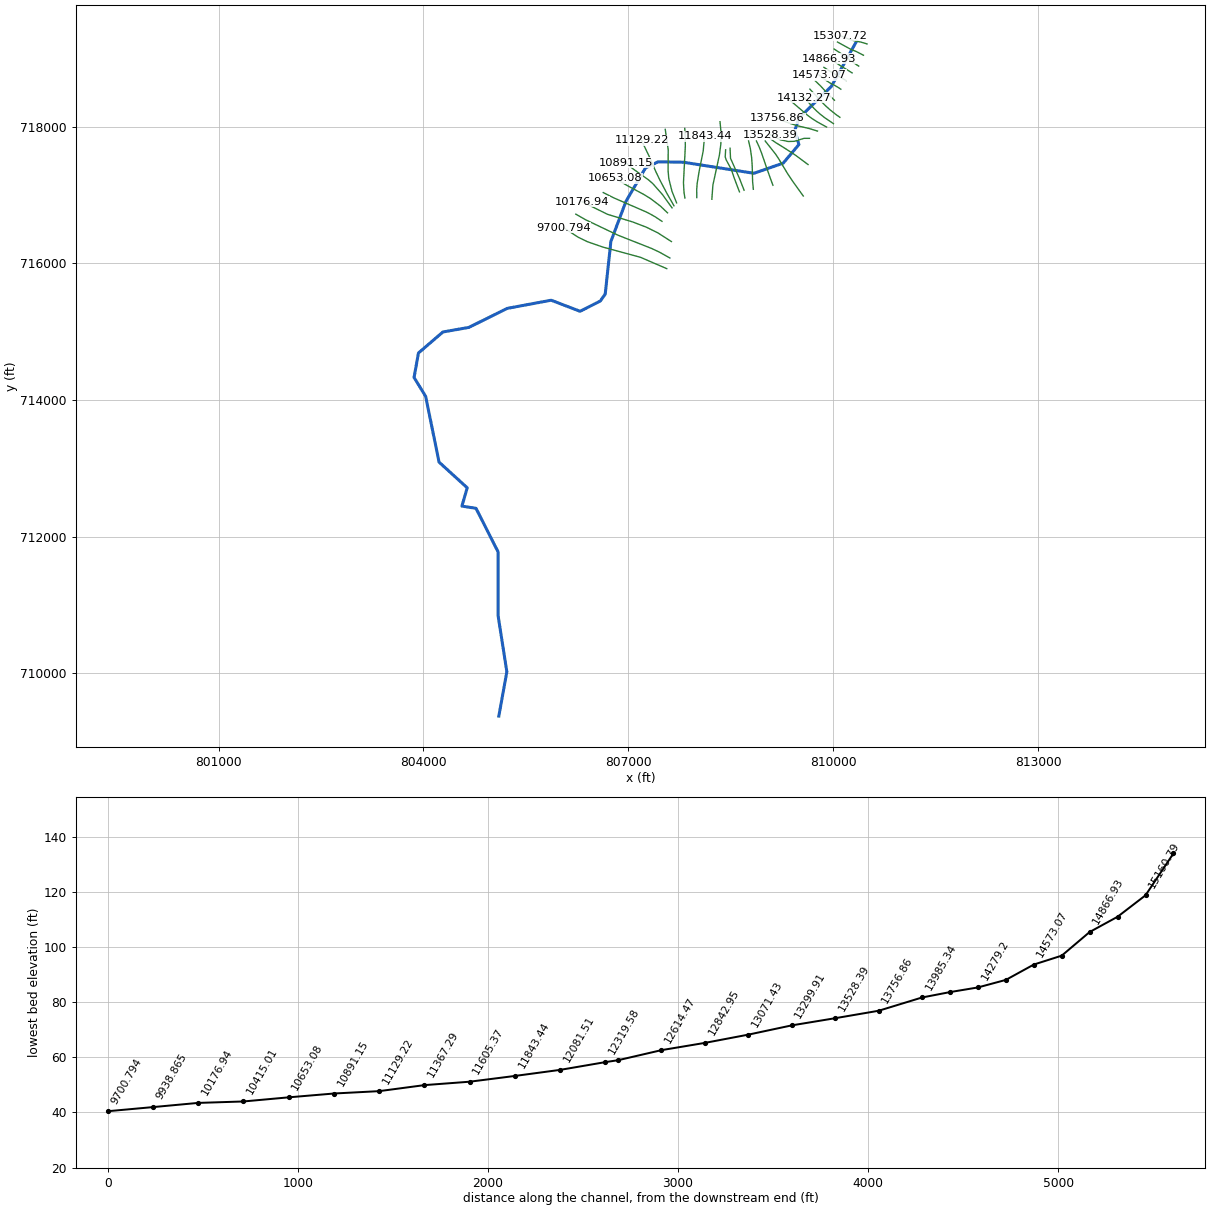
--- 6869_ras.prj (project) ---

Proj Title=6869
Current Plan=p01
Default Exp/Contr=0.3,0.1
English Units
Geom File=g01
Flow File=f01
Plan File=p01
Y Axis Title=Elevation
X Axis Title(PF)=Main Channel Distance
X Axis Title(XS)=Station
BEGIN DESCRIPTION:
RFD model 6869 exported to HEC-RAS
END DESCRIPTION:

--- 6869_ras.p01 (plan) ---

Plan Title=Plan 01
Program Version=4.10
Short Identifier=Plan 01
Geom File=g01
Flow File=f01
Subcritical Flow
Calc Critical at every XS
Secant Critical Depth

--- 6869_ras.f01 (steady flow) ---

Flow Title=Flow 01
Program Version=5.01
Number of Profiles= 6
Profile Names=10yr,25yr,50yr,100yr,100plus,500yr
River Rch & RM=6869,38,15307.72
 1541.17 2634.96 3721.76 4781.62 6981.17 9444.51
River Rch & RM=6869,38,15160.79
 1542.06 2636.54 3724.04 4784.59  6985.5 9449.74
River Rch & RM=6869,38,15013.86
 1544.93 2641.59 3731.31 4794.08 6999.35 9466.47
River Rch & RM=6869,38,14866.93
 1554.18 2657.98 3755.02 4825.16 7044.73  9521.8
River Rch & RM=6869,38,   14720
 1555.79 2660.81  3759.1 4830.49 7052.51 9531.19
River Rch & RM=6869,38,14573.07
 1557.89 2664.54 3764.49 4837.54  7062.8 9543.69
River Rch & RM=6869,38,14426.14
 1560.67 2669.46 3771.62 4846.89 7076.46 9560.36
River Rch & RM=6869,38, 14279.2
 1562.26 2672.28 3775.67 4852.19  7084.2 9569.73
River Rch & RM=6869,38,14132.27
 1563.29  2674.1 3778.32 4855.68 7089.29 9575.97
River Rch & RM=6869,38,13985.34
 1659.04 2840.93 4017.06 5165.56 7541.7110111.21
River Rch & RM=6869,38,13756.86
 1661.57 2845.44  4023.6 5174.16 7554.2710126.49
River Rch & RM=6869,38,13528.39
  1663.6 2849.06 4028.86 5181.06 7564.35 10138.7
River Rch & RM=6869,38,13299.91
 1676.79 2872.46 4062.72 5225.47 7629.1810216.92
River Rch & RM=6869,38,13071.43
 1996.99 3434.68 4871.36 6279.71 9168.3712021.78
River Rch & RM=6869,38,12842.95
 1997.98 3436.43 4873.89 6283.03 9173.2312027.49
River Rch & RM=6869,38,12614.47
 2003.39 3446.04 4887.82 6301.31 9199.9112058.87
River Rch & RM=6869,38,12385.99
 2007.82 3453.91 4899.22 6316.26 9221.7412084.52
River Rch & RM=6869,38,12319.58
 2009.13 3456.24 4902.59 6320.69 9228.2112092.12
River Rch & RM=6869,38,12081.51
 2013.28 3463.66  4913.4 6334.93 9248.9912116.79
River Rch & RM=6869,38,11843.44
 2135.64 3681.25  5228.9 6749.17 9853.7812824.97
River Rch & RM=6869,38,11605.37
  2166.1 3735.78 5308.29 6853.7910006.5413004.45
River Rch & RM=6869,38,11367.29
 2187.53 3774.23 5364.36 6927.7910114.5713131.54
River Rch & RM=6869,38,11129.22
 2191.26 3780.92 5374.12 6940.6510133.3513153.59
River Rch & RM=6869,38,10891.15
  2224.5 3840.75 5461.53 7056.1810302.0313352.32
River Rch & RM=6869,38,10653.08
 2227.44 3846.02 5469.21 7066.3210316.8213369.66
River Rch & RM=6869,38,10415.01
 2230.04  3850.7 5476.04 7075.3510330.0113385.18
River Rch & RM=6869,38,10176.94
 2265.54 3914.85 5570.01 7199.8110511.7213599.79
River Rch & RM=6869,38,9938.865
 2268.14 3919.53 5576.83 7208.8210524.88 13615.2
River Rch & RM=6869,38,9700.794
 2271.75 3926.04 5586.36 7221.4510543.3213636.94
River Rch & RM=6869,38,9462.722
 2276.54 3934.71 5599.06 7238.2710567.8813665.91
River Rch & RM=6869,38, 9224.65
 2277.44 3936.33 5601.44 7241.4210572.4813671.34
River Rch & RM=6869,38,8986.579
 2338.86 4046.22 5761.42 7452.2210880.2414028.68
River Rch & RM=6869,38,8620.846
 2342.73 4053.22 5771.67  7465.810900.0614051.96
River Rch & RM=6869,38,7826.628
 2350.32 4066.94 5791.77 7492.4210938.9414097.57
River Rch & RM=6869,38,7365.689
 2393.23 4144.87 5906.29 7644.5411161.0214359.42
River Rch & RM=6869,38,6904.749
 2402.28 4161.37  5930.6 7676.8911208.2614415.28
River Rch & RM=6869,38, 6443.81
 2411.02 4177.32 5954.09 7708.1711253.9314469.29
River Rch & RM=6869,38,6171.788
 2419.55 4192.91 5977.09 7738.8311298.6914522.34
Boundary for River Rch & Prof#=6869,38,1
Up Type= 0
Dn Type= 2
Boundary for River Rch & Prof#=6869,38,2
Up Type= 0
Dn Type= 2
Boundary for River Rch & Prof#=6869,38,2
Up Type= 0
Dn Type= 2
Boundary for River Rch & Prof#=6869,38,2
Up Type= 0
Dn Type= 2
Boundary for River Rch & Prof#=6869,38,2
Up Type= 0
Dn Type= 2
Boundary for River Rch & Prof#=6869,38,2
Up Type= 0
Dn Type= 2

--- 6869_ras.g01 (geometry) ---

Geom Title=6869
Program Version=4.10

River Reach=6869,38
Reach XY= 30
810343.377943726719254.936009413809973.852079779718593.166362633
809499.751799168718129.619709197809438.072298736717946.089213216
809498.139221611717741.189529596809267.869574845717468.308889434
 808839.67957795717320.188871304807808.077492953717481.752379338
807436.510949939717488.637250719807251.840354683717398.323103392
806966.641752305 716911.60206506 806744.53084621716321.944681561
806661.703426007715551.646691174806589.670282961715449.254523254
806293.639047296715298.900106009805870.084031286715461.248048567
805225.986809077 715341.45638189804664.808098822715063.095250303
804284.676860692714996.161161936803926.807393866714688.449432551
803862.155994893 714329.67775414804031.877293381714053.352532145
804228.475439313 713090.09442082804640.801828239712714.226365238
804562.676828238712445.997198571804769.274050473712413.879143027
805092.448787692711776.702904273805093.926828237710834.886087459
805221.010161549710019.955531906805103.822661582709371.518031922

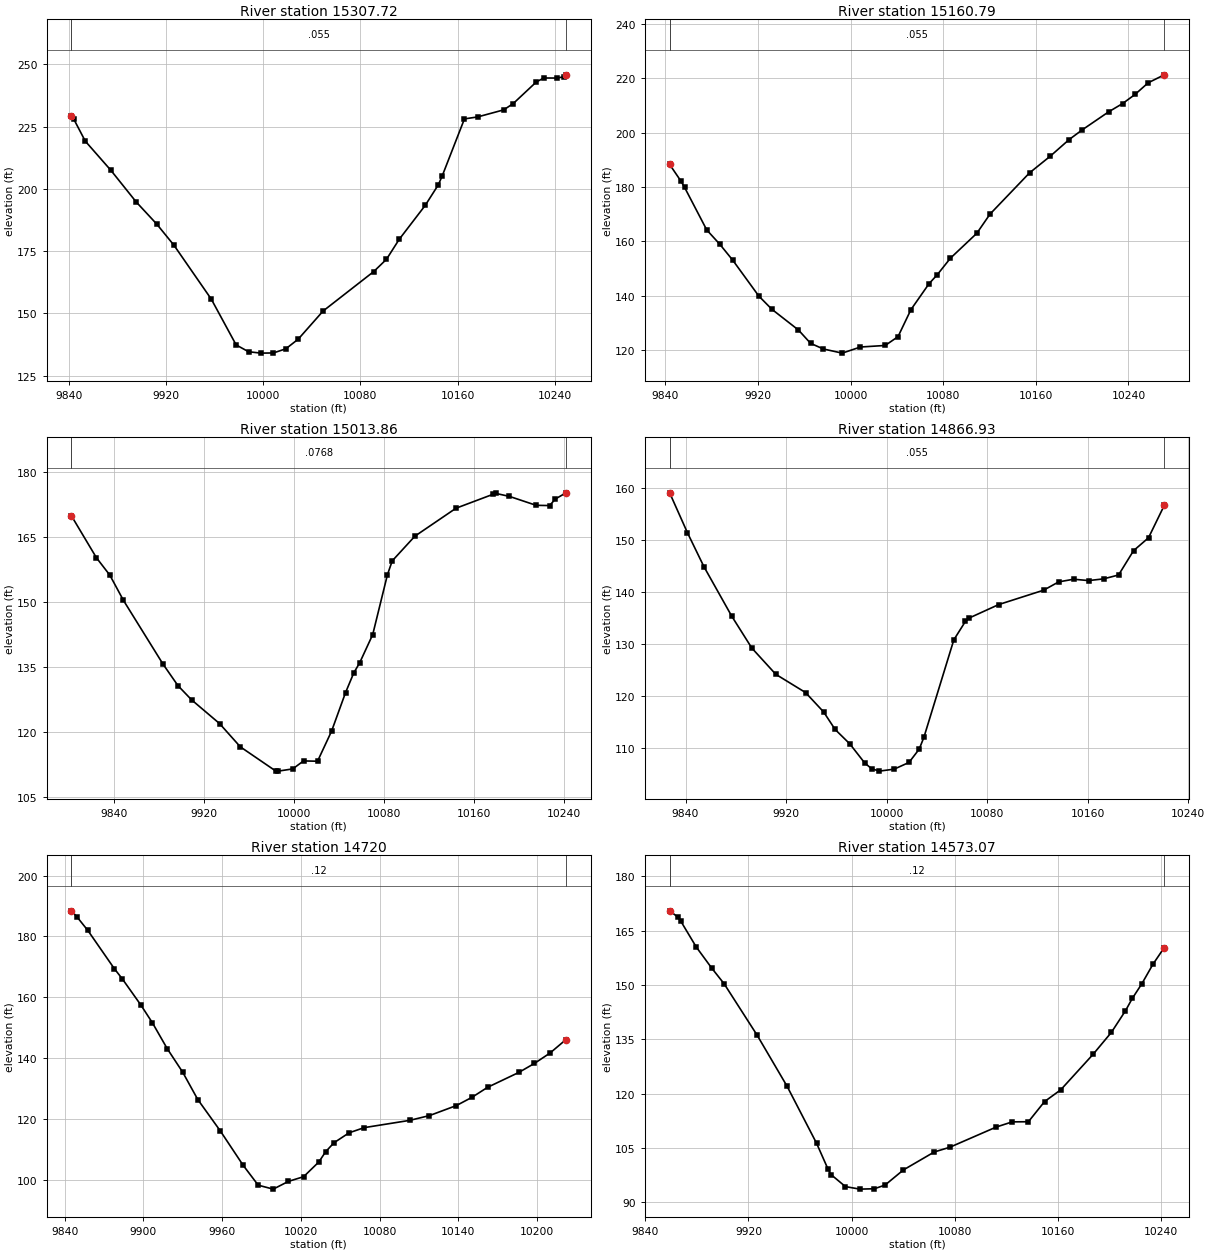
Type RM Length L Ch R = 1 ,15307.72,146.931200,146.931200,146.931200
XS GIS Cut Line= 6
810495.777086612719214.363339484810407.972380167719240.685520662
810289.497604486719265.656207294810230.492353613719283.571948927
810147.687238299719316.712752845810108.624054954719335.587869589
#Sta/Elev= 30
9842.142229.40019844.074228.01049853.556219.14699874.724 207.3739895.462 194.722
9912.349185.84339926.569 177.3179957.305155.65579977.719137.30289987.927134.5616
9998.134134.002210008.36134.0756 10018.6135.733310028.83139.6222 10049.3150.9203
10090.99166.775810101.44171.691510111.89179.688410133.29  193.3110144.06201.5638
10147.36205.2325 10165.6228.076910176.37228.855310197.91231.702410205.79234.2512
10224.84242.948310230.99244.500110242.09244.477810247.82245.067410249.18245.7737
#Mann= 3 , 0 , 0
9842.142   0.055       09842.142   0.055       010249.18   0.055       0
#XS Ineff= 2 , 0
       0                               0
Bank Sta=9842.142,10249.18
Exp/Cntr=0.3,0.1

Type RM Length L Ch R = 1 ,15160.79,146.931200,146.931200,146.931200
XS GIS Cut Line= 6
810443.481120638 719049.10808701810344.536927372719100.090630923
810319.926666467719111.372067151810278.342579319719126.205552074
810256.809742783719136.499578309810062.824478448719242.227194389
#Sta/Elev= 30
9843.622188.29459853.163182.31139856.485179.88629875.662164.18959886.911158.9241
9898.161153.02419920.659139.82339931.909134.96329954.929127.3006 9965.42122.3936
9976.421120.3224 9992.72118.793210008.49121.047810029.86 121.61510040.94124.8636
10052.08134.810910067.78144.400610074.86147.683810086.25153.789810109.02162.9523
10120.41170.003410154.58185.211510172.27191.278110188.74197.457810200.13201.0622
10222.91 207.68910234.96210.736210245.69214.085510257.08218.391810270.95221.3237
#Mann= 3 , 0 , 0
9843.622   0.055       09843.622   0.055       010270.95   0.055       0
#XS Ineff= 2 , 0
       0                               0
Bank Sta=9843.622,10270.95
Exp/Cntr=0.3,0.1

Type RM Length L Ch R = 1 ,15013.86,146.931200,146.931200,146.931200
XS GIS Cut Line= 6
 810373.87701623718890.204310321810347.843283257718906.475816562
810282.403365677718951.138040447810153.411742303719046.647546431
 810097.61372301719085.705772367810012.687828164719140.025561101
#Sta/Elev= 30
9802.364169.94629824.624160.24959836.506156.24659848.613150.41419883.664135.7411
9897.041130.73479909.148127.45849933.939121.99629952.418116.61899983.693  111.07
9986.049111.0117    9999111.526310008.56113.365910021.01113.296410033.46120.2236
10045.92 129.15510053.24133.706210058.37135.974610070.03142.529310083.06156.3017
10087.36159.538410107.48165.234910144.01171.688910176.71174.886210179.62175.0932
10191.49174.418410215.23 172.358 10227.1172.300610232.39173.837610241.72175.2416
#Mann= 3 , 0 , 0
9802.364  0.0768       09802.364  0.0768       010241.72  0.0768       0
#XS Ineff= 2 , 0
       0                               0
Bank Sta=9802.364,10241.72
Exp/Cntr=0.3,0.1

Type RM Length L Ch R = 1 ,14866.93,146.931100,146.931100,146.931100
XS GIS Cut Line= 5
810277.059795631718790.689009275810130.951535709718880.759039347
810129.252975329 718881.81492411810107.908914633718895.143291467
 809944.48565533719000.998054918
#Sta/Elev= 30
 9827.36159.07279841.527151.38639854.632144.8541 9876.77135.31489892.744129.1805
  9911.8124.12699935.507120.60689949.913 116.8629959.002113.50459970.749110.7128
9982.497107.06649988.025105.93969994.244105.476910006.01105.8603 10017.8107.1501
10025.89109.708910029.63111.973410053.46130.760210062.69134.316310065.37134.9301
 10089.2137.557710124.95140.327310136.86141.918110148.77142.435510160.69142.1708
 10172.6142.502310184.52143.250310196.43147.929310208.35150.417410220.87156.6456
#Mann= 3 , 0 , 0
 9827.36   0.055       0 9827.36   0.055       010220.87   0.055       0
#XS Ineff= 2 , 0
       0                               0
Bank Sta=9827.36,10220.87
Exp/Cntr=0.3,0.1

Type RM Length L Ch R = 1 ,   14720,146.931200,146.931200,146.931200
XS GIS Cut Line= 5
810188.644107292718678.798286068810054.950916751718755.063125632
810053.221989305718756.068516048809962.182319638718808.607021404
809864.764872226 718871.28841361
#Sta/Elev= 30
9845.084188.43579849.279186.4733  9857.6181.98869877.782169.42079883.817166.0853
9897.964157.48659906.842151.58079918.145143.06449929.868135.3745 9941.38126.3697
9958.509116.06569975.918104.75429987.431 98.18999998.87396.8936410010.4999.44614
10022.04100.985910033.58105.808510038.88109.232110045.13112.137210056.68 115.419
10068.22117.122410102.86119.510410117.93121.084910138.43 124.38110150.33127.0996
10162.22130.3901   10186135.277910197.89138.241810209.78141.657610221.95146.0959
#Mann= 3 , 0 , 0
9845.084    0.12       09845.084    0.12       010221.95    0.12       0
#XS Ineff= 2 , 0
       0                               0
Bank Sta=9845.084,10221.95
Exp/Cntr=0.3,0.1

Type RM Length L Ch R = 1 ,14573.07,146.931200,146.931200,146.931200
XS GIS Cut Line= 6
810112.183904454718551.618979539810074.407171591718576.630588856
810021.549058538718607.802573968809953.782322912718642.170994097
 809891.35536227718683.868809903809791.480551107718760.439571955
#Sta/Elev= 30
9858.844170.50599864.969168.8457 9867.46167.67019879.453160.53359891.447 154.705
9901.197150.31529926.681136.1728  9949.9122.07929972.832106.29159981.66399.19327
9984.003 97.67659995.17494.3597410006.3493.6618610017.6193.7671910025.9294.78386
10040.1398.9604110064.09103.923510076.12105.222710112.19110.813510124.54112.2333
10137.07112.2698 10149.6117.837310162.13121.076510187.19130.861610201.43136.9454
10212.38142.924510217.63146.301810225.16150.4302 10233.7155.778110242.43160.3498
#Mann= 3 , 0 , 0
9858.844    0.12       09858.844    0.12       010242.43    0.12       0
#XS Ineff= 2 , 0
       0                               0
Bank Sta=9858.844,10242.43
Exp/Cntr=0.3,0.1

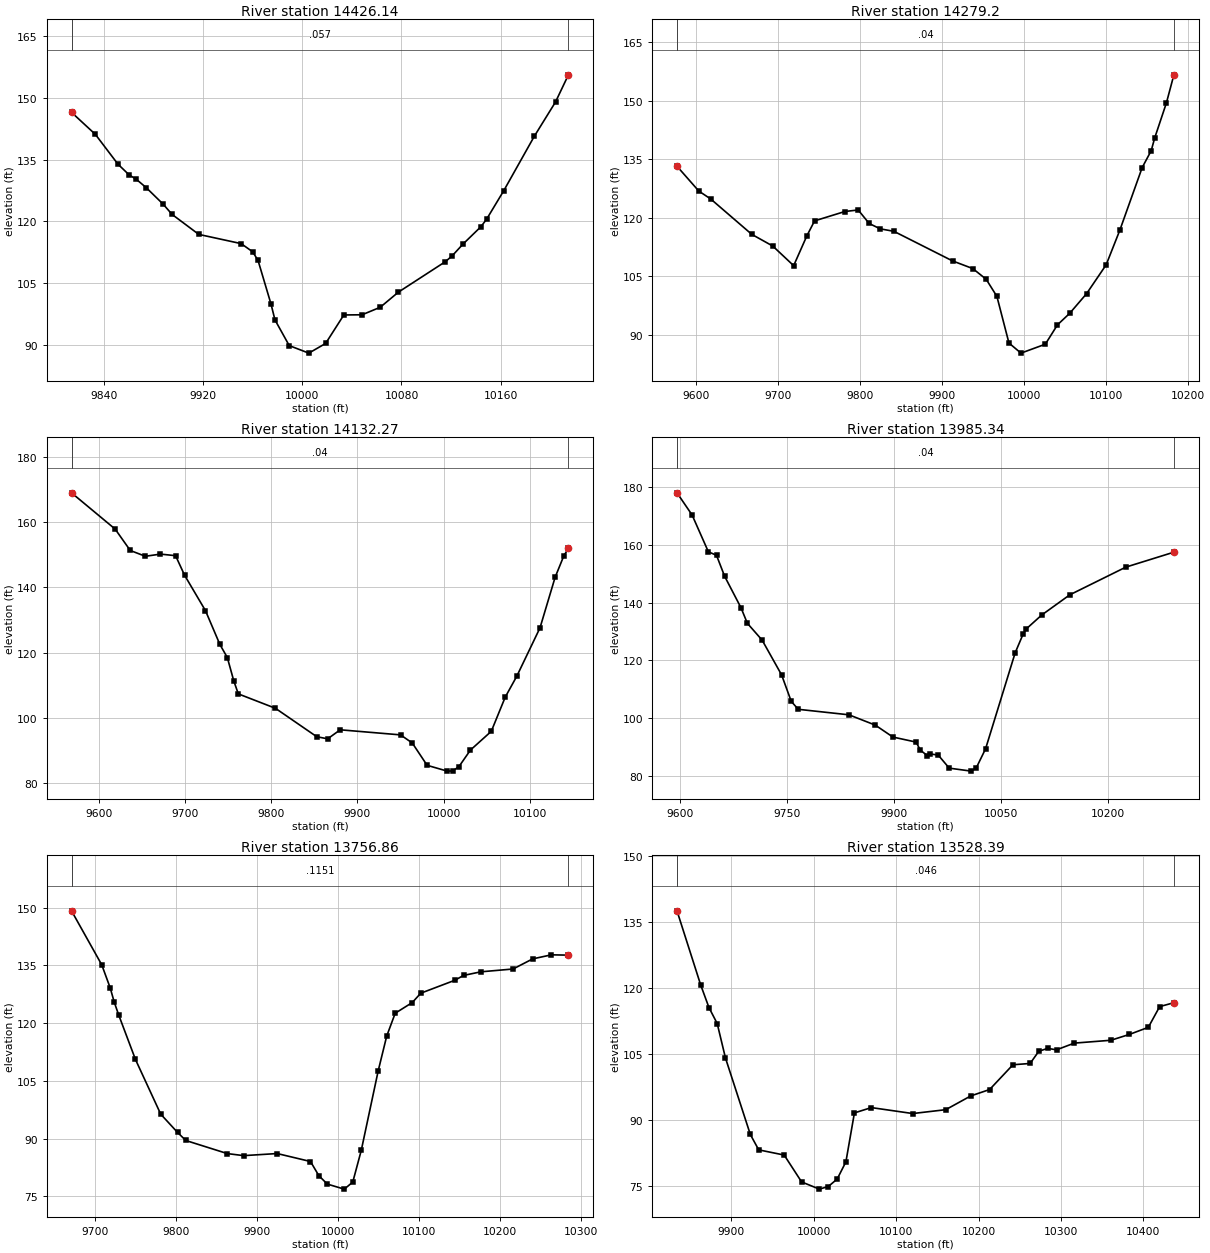
Type RM Length L Ch R = 1 ,14426.14,146.931200,146.931200,146.931200
XS GIS Cut Line= 6
810019.269414122 718389.67645529810015.459698165718392.900287941
809966.843818118718438.119609024809928.803590771718476.906367971
809815.536995572718598.733860841809737.509864638718674.086473581
#Sta/Elev= 30
9814.048146.44399833.323141.08669851.487133.88119860.637131.2433 9866.17130.2463
9874.294128.18699888.067 124.1439895.071 121.718 9916.63116.86499950.785114.6299
9960.092112.64159964.405 110.5519974.821100.01859978.02596.16012 9989.5589.91656
10005.3388.0948110018.88  90.44410033.5597.3431510048.2297.3865810062.8999.20533
10077.56102.880310115.13110.205810120.76111.629510129.52114.492910143.92118.6914
10148.56 120.50910162.46127.454410187.11 140.65310204.17148.945310214.58155.5313
#Mann= 3 , 0 , 0
9814.048   0.057       09814.048   0.057       010214.58   0.057       0
#XS Ineff= 2 , 0
       0                               0
Bank Sta=9814.048,10214.58
Exp/Cntr=0.3,0.1

Type RM Length L Ch R = 1 , 14279.2,146.931200,146.931200,146.931200
XS GIS Cut Line= 6
810098.645276379718139.726975044 810048.20017375718175.072968704
809959.910147154718244.798658002809901.206566163718296.826976655
 809842.33941985718354.498049813809658.637405783718552.879412004
#Sta/Elev= 30
9577.187133.19859603.803126.8396 9618.27124.81959668.346115.75769693.831112.7763
9719.315107.74949735.476115.4174  9744.8119.21639781.743121.61379797.934122.0053
9811.296  118.559824.658117.17989841.406116.54289912.823108.96959937.569106.9994
9953.831  104.279966.90399.882839981.57187.950339996.23885.35875 10025.987.64354
10040.7292.6078710055.5495.5373210076.13 100.57710100.01107.968610116.77116.8909
10143.87132.854410154.89137.194810159.14140.445210173.43149.434210182.52 156.602
#Mann= 3 , 0 , 0
9577.187    0.04       09577.187    0.04       010182.52    0.04       0
#XS Ineff= 2 , 0
       0                               0
Bank Sta=9577.187,10182.52
Exp/Cntr=0.3,0.1

Type RM Length L Ch R = 1 ,14132.27,146.931200,146.931200,146.931200
XS GIS Cut Line= 6
810003.662474873718047.318027284809872.404942281718136.608524211
809804.791307914718190.035085206809760.735676407718229.312958343
809721.299882256718268.207535874809574.241425689718428.767676612
#Sta/Elev= 30
9567.855168.96629618.556157.84719636.097151.29329653.639 149.522 9671.18150.1845
9688.721149.69999699.124143.73619723.467132.83819740.161122.49529748.809118.4859
 9756.29 111.3499761.554107.34679804.679102.93039852.71294.212199865.34293.57171
9879.92296.334939950.016 94.77939963.59692.298459980.86585.4491110004.2783.66936
10010.5783.7264210017.7385.0239210031.19 90.130610055.3895.8703710071.58106.3491
10085.05112.787510111.97127.594410129.52143.0846 10139.7149.691510144.96 151.937
#Mann= 3 , 0 , 0
9567.855    0.04       09567.855    0.04       010144.96    0.04       0
#XS Ineff= 2 , 0
       0                               0
Bank Sta=9567.855,10144.96
Exp/Cntr=0.3,0.1

Type RM Length L Ch R = 1 ,13985.34,228.478100,228.478100,228.478100
XS GIS Cut Line= 6
809903.567404956717997.189535871809767.016421884 718072.62955974
809688.013285995718123.131036267809627.871226341718167.790082768
809567.579895347718218.787967548809343.671571583718409.515924767
#Sta/Elev= 30
9595.353177.96019616.566170.29999639.415157.5663 9650.84156.35669662.264149.0976
9685.114138.27129694.222132.82379714.901127.02259742.237115.00749755.759105.8587
9765.619103.09379836.831101.19119873.78797.631099898.57993.498739931.19791.75223
9936.89189.024729946.68187.096169949.98987.689629962.16687.27131 9977.65 82.7476
10008.5681.7143810015.5482.8043410028.6889.4269610070.25122.640110081.22 129.006
10085.67130.860610107.49135.695510146.89142.678510225.71 152.27210293.13157.4361
#Mann= 3 , 0 , 0
9595.353    0.04       09595.353    0.04       010293.13    0.04       0
#XS Ineff= 2 , 0
       0                               0
Bank Sta=9595.353,10293.13
Exp/Cntr=0.3,0.1

Type RM Length L Ch R = 1 ,13756.86,228.478200,228.478200,228.478200
XS GIS Cut Line= 6
809770.278376368717938.231629909809650.995875247717975.003495551
809488.673133851718012.924372821809377.513056246718047.403102917
 809261.74998288718088.895170553809186.359036517718124.133814157
#Sta/Elev= 30
9670.603149.17799707.975135.15729718.429129.15969723.465125.42619728.838122.1796
9749.658110.56459780.88796.362559801.62391.634199811.89289.525849863.23886.12403
9883.36685.593869924.85486.135569965.99284.067929976.428 80.35269986.86378.19577
10007.7776.8946410018.2678.7322910028.7586.9636510049.72107.654910060.21116.6489
10070.69122.578810091.76125.352810102.32127.785510144.55131.152210155.16132.3977
10176.61133.338210216.37134.069210240.66136.701510263.82137.7494 10284.8137.6691
#Mann= 3 , 0 , 0
9670.603  0.1151       09670.603  0.1151       0 10284.8  0.1151       0
#XS Ineff= 2 , 0
       0                               0
Bank Sta=9670.603,10284.8
Exp/Cntr=0.3,0.1

Type RM Length L Ch R = 1 ,13528.39,228.478100,228.478100,228.478100
XS GIS Cut Line= 6
809653.737723401717832.047827062809573.905813062717832.003211517
809428.638443751717787.932635012809340.299442783717785.590497251
809224.589650291717811.038358119 809078.75753405717884.205367777
#Sta/Elev= 30
9833.986137.56749862.765120.67869872.779115.54329882.795111.89839892.811104.0669
9922.99586.638829933.16583.139299964.07681.953319985.233 75.8353 10006.874.19476
 10017.674.7899510028.3976.4853810038.9980.4075210049.3291.5522410069.8992.76132
10120.0891.4068510160.1592.2840810190.4995.4150310213.4296.8740510241.72102.5173
10262.58 102.80910273.08105.585410283.83106.2464 10294.6105.913210316.14107.4416
 10360.6 108.09410383.18109.430410406.03111.0417 10419.8 115.75910437.06116.6432
#Mann= 3 , 0 , 0
9833.986   0.046       09833.986   0.046       010437.06   0.046       0
#XS Ineff= 2 , 0
       0                               0
Bank Sta=9833.986,10437.06
Exp/Cntr=0.3,0.1

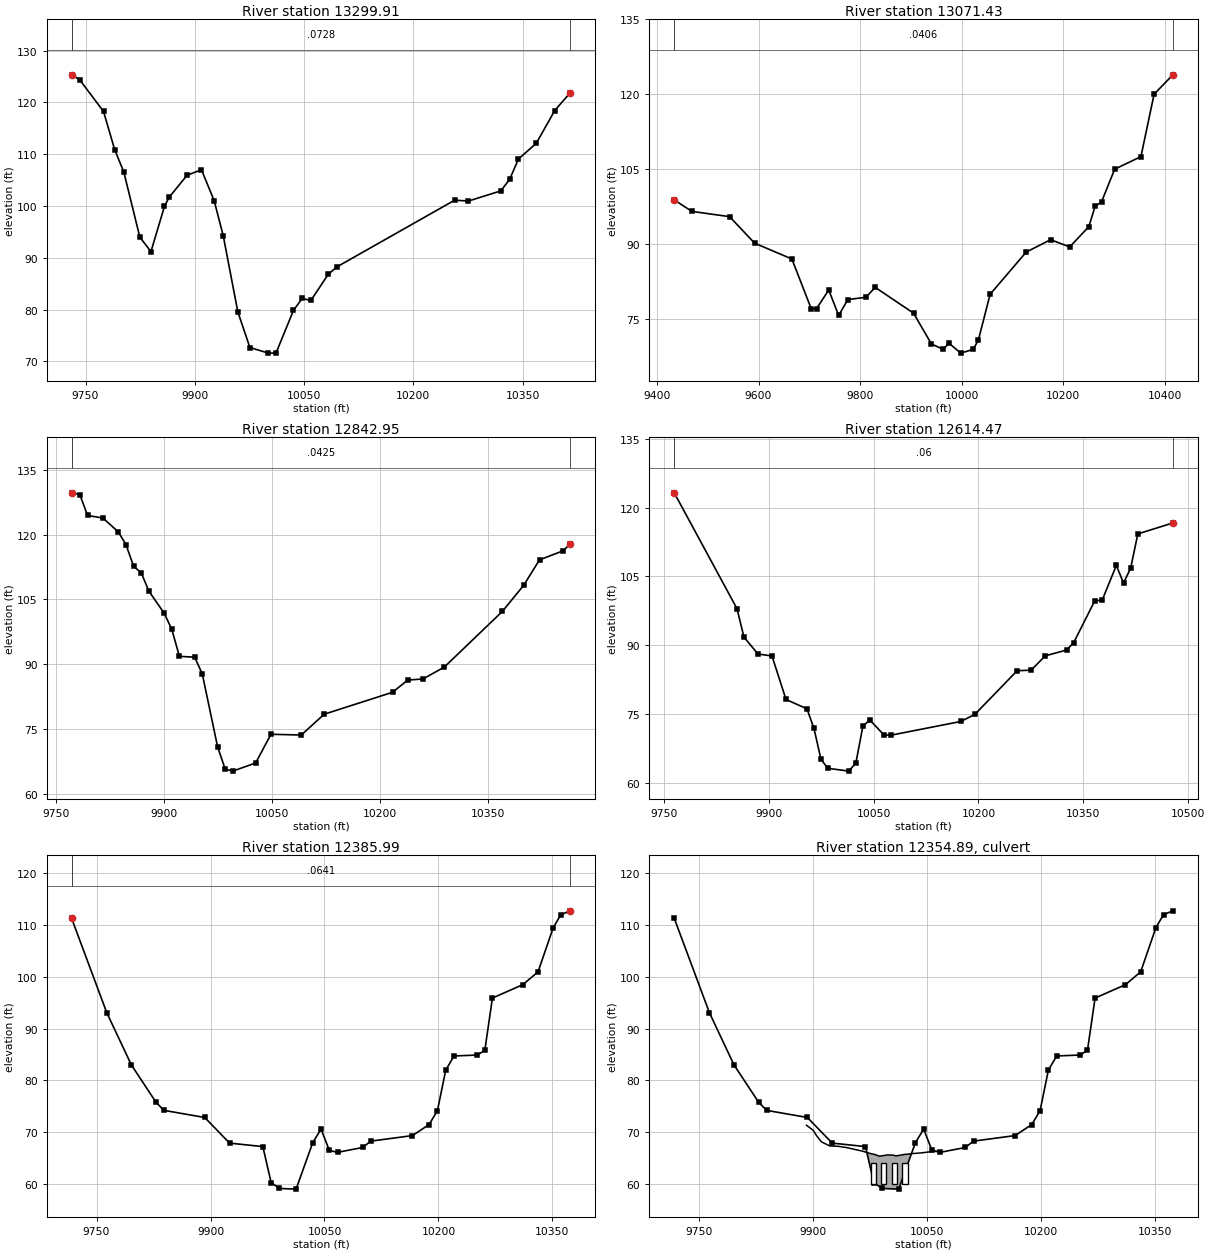
Type RM Length L Ch R = 1 ,13299.91,228.478200,228.478200,228.478200
XS GIS Cut Line= 6
809631.911432921717448.361001149809448.817977238 717584.48470814
809307.313343908717677.190295123809160.643634181717768.385537194
809108.815992594717804.160619865 809068.27544894717835.725724115
#Sta/Elev= 30
9730.854125.32589741.771124.4058 9774.66118.26029789.947110.89789802.544106.5515
9824.52793.973289839.78291.193799858.36799.938469864.576101.65029889.369105.9404
9909.128106.99829926.559101.00799938.95694.283599959.01679.568379975.58472.67301
   1000171.5896910011.4971.6179410035.3879.8409510047.33 82.142210059.27 81.7542
10083.1686.8150810095.1188.2511510256.61101.118710275.54100.9557 10319.9102.9107
10332.05 105.11910344.21109.065910368.71112.113310394.05 118.43310415.25 121.868
#Mann= 3 , 0 , 0
9730.854  0.0728       09730.854  0.0728       010415.25  0.0728       0
#XS Ineff= 2 , 0
       0                               0
Bank Sta=9730.854,10415.25
Exp/Cntr=0.3,0.1

Type RM Length L Ch R = 1 ,13071.43,228.478100,228.478100,228.478100
XS GIS Cut Line= 6
809562.398707368716987.119849144809411.434507825717196.814295434
809333.770191106717312.795500464809206.325399896717525.464754472
809156.645400071717600.870000822809004.047175384717793.598923743
#Sta/Elev= 30
9434.02898.900689468.62696.591989543.084 95.54299592.30890.234679665.729 87.0695
9703.98877.07891 9714.3177.131719738.37980.868389757.90575.769869775.87878.94037
9811.82379.412629829.79681.392459905.34676.232359940.61570.062639963.727 68.9931
9975.28470.209949998.39668.2294610023.0968.9858510033.1170.8622410056.2780.01241
10127.3188.4542510175.4490.9285110213.0189.4851110250.5893.52339 10263.197.62733
10275.6998.4988910301.55105.039110353.29107.555410379.16120.034510416.15123.9238
#Mann= 3 , 0 , 0
9434.028  0.0406       09434.028  0.0406       010416.15  0.0406       0
#XS Ineff= 2 , 0
       09893.241                       0
Bank Sta=9434.028,10416.15
Exp/Cntr=0.3,0.1

Type RM Length L Ch R = 1 ,12842.95,228.478200,228.478200,228.478200
XS GIS Cut Line= 6
809117.971210041717144.232009967809088.454542269717222.869238509
809029.406591104717389.062727823808950.822834757717618.142376551
808917.565178399  717702.0283784808875.851894152717793.598923743
#Sta/Elev= 30
 9771.08129.69649782.582129.28079793.263124.45159814.626123.85669835.988120.6561
 9846.67117.71829857.335112.68359867.944111.17139878.553106.92669899.771101.8252
 9910.3898.116989920.98991.821019942.20791.629799952.81687.764199974.03470.92819
9984.64365.715799995.25265.2357510027.1367.13469 10048.373.7700710090.5873.59956
 10122.3 78.412610217.4583.5004610238.5986.3246610259.74 86.581310289.4389.33298
 10370.2 102.23110399.94108.307710421.82114.177210454.92116.285910464.51117.8821
#Mann= 3 , 0 , 0
 9771.08  0.0425       0 9771.08  0.0425       010464.51  0.0425       0
#XS Ineff= 2 , 0
       0                               0
Bank Sta=9771.08,10464.51
Exp/Cntr=0.3,0.1

Type RM Length L Ch R = 1 ,12614.47,228.478100,228.478100,228.478100
XS GIS Cut Line= 6
808830.869479804 717085.76178492808820.255572088 717197.19785047
808814.438900943717426.314059773808806.377838868717546.233620194
808786.934683737717682.371899359808761.246255268717793.598923743
#Sta/Elev= 30
9764.937123.20949854.61398.00016 9864.6591.780379884.70488.108979904.72487.68147
9924.74578.212999954.77676.166649964.77771.904089974.77865.162999984.77863.21469
10014.7862.6021110024.7864.4260110034.7872.4188710044.7973.7346310064.7970.48348
10074.7970.4257410174.9573.4222510194.9974.9720610255.2884.4630710275.4384.59559
10295.5887.7136910325.9688.97112 10336.190.5492410366.5499.7483710376.7799.77311
10397.24107.405510407.47103.5395 10417.7106.815410427.93114.258410478.03116.6484
#Mann= 3 , 0 , 0
9764.937    0.06       09764.937    0.06       010478.03    0.06       0
#XS Ineff= 2 , 0
       0                               0
Bank Sta=9764.937,10478.03
Exp/Cntr=0.3,0.1

Type RM Length L Ch R = 1 ,12385.99,66.413100,66.413100,66.413100
XS GIS Cut Line= 5
808695.421770871717071.796305254 808629.35695985717240.798501909
 808577.79445982717356.944335252 808496.54445982717539.756835237
808490.077445924717687.282876909
#Sta/Elev= 30
9717.142111.3126 9763.5393.02424 9795.7482.981919828.166 75.75629838.68874.17581
9892.37372.799779925.07867.843389968.84267.171079979.78360.219999990.72459.07333
10012.61 58.946510034.4967.9043910045.4370.5550110056.38 66.429710067.3266.06293
10100.1566.9968410111.0968.2305910165.8169.30139 10187.771.4354910198.6474.11833
10209.58 81.963110220.5284.69574   1025184.8708710261.0185.7745410271.0295.89119
10311.0698.4842710331.07100.965810351.09109.5106 10361.1112.0116 10373.4112.7585
#Mann= 3 , 0 , 0
9717.142  0.0641       09717.142  0.0641       0 10373.4  0.0641       0
#XS Ineff= 2 , 0
       0                               0
Bank Sta=9717.142,10373.4
Exp/Cntr=0.3,0.1

Type RM Length L Ch R = 2 ,12354.89,,,
Bridge Culvert--1,0,-1,-1, 0
Deck Dist Width WeirC Skew NumUp NumDn MinLoCord MaxHiCord MaxSubmerge Is_Ogee
22.207,22,2.6,0,25,25, , , 0.95, 0, 0,0,,
 9891.18 9900.07 9904.56 9910.95 9921.84 9929.87 9932.72 9943.61 9954.49 9955.19
 9965.38 9976.27 9980.50 9987.15 9998.0410005.8110008.9210019.8110030.6910031.12
10041.5810052.4610056.4310063.3510064.11
   71.30   70.32   69.26   68.08   67.30   67.25   67.23   66.99   66.64   66.61
   66.27   65.79   65.68   65.32   65.56   65.51   65.37   65.64   65.83   65.83
   65.94   66.14   66.20   66.28   66.30
                                                                                
                                                                                
                                        
 9891.18 9900.07 9904.56 9910.95 9921.84 9929.87 9932.72 9943.61 9954.49 9955.19
 9965.38 9976.27 9980.50 9987.15 9998.0410005.8110008.9210019.8110030.6910031.12
10041.5810052.4610056.4310063.3510064.11
   71.30   70.32   69.26   68.08   67.30   67.25   67.23   66.99   66.64   66.61
   66.27   65.79   65.68   65.32   65.56   65.51   65.37   65.64   65.83   65.83
   65.94   66.14   66.20   66.28   66.30
                                                                                
                                                                                
                                        
BR Coef=-1 , 0 , 0 ,, 0 ,,,0.8,-1,,0,
WSPro=,,,, 1 ,,,, 0 ,,,, 0 ,,,,-1 ,-1 ,-1 , 0 , 0 , 0 , 0 , 0
Multiple Barrel Culv=2,4,7,22,0.013,0.5,1,8,3,60,58,4,Culvert #1, 0, 22.207
 9979.00 9979.00 9993.00 9993.0010007.0010007.0010021.0010021.00
Culvert Bottom n=0.013
BC Design=,, 0 ,, 0 ,,,,,,

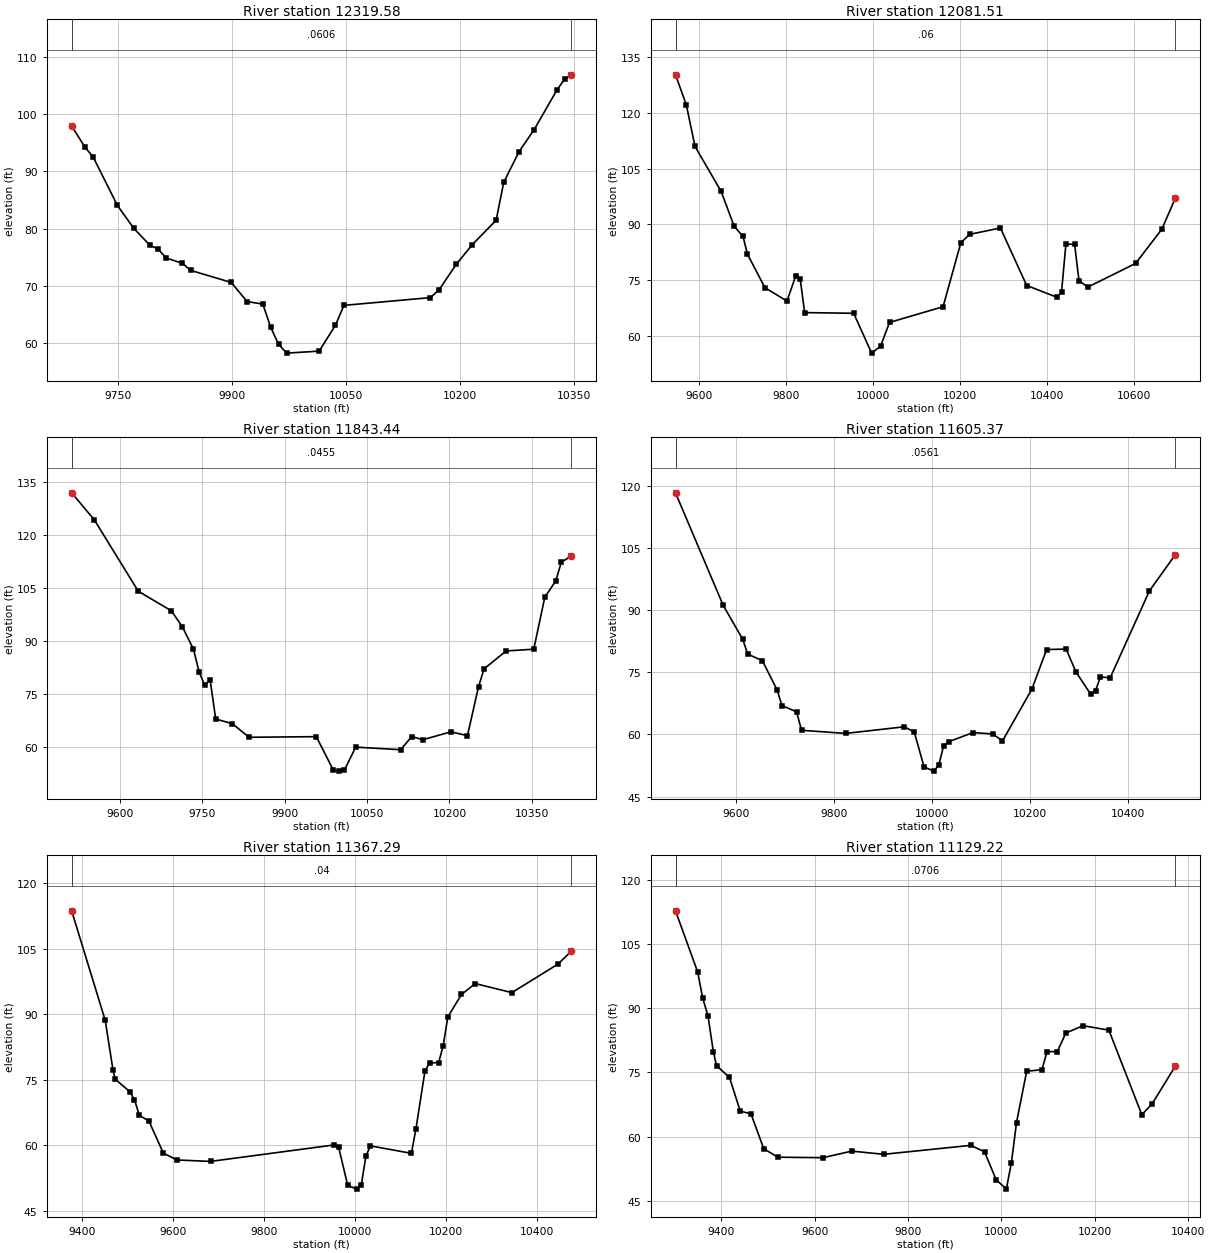
Type RM Length L Ch R = 1 ,12319.58,238.071600,238.071600,238.071600
XS GIS Cut Line= 6
 808627.40383485717048.697807491808551.014945924717249.218640819
808508.523626477717377.256835237808434.565293133717513.715168595
808418.940293133717560.069335252808424.973279238717663.845376909
#Sta/Elev= 30
 9688.8497.928139706.28594.206269716.98692.527829749.08984.036869770.49180.06195
9791.89377.082979802.59476.427529813.29574.865239834.69773.929769845.39872.70685
9898.90470.594689919.76267.260619940.47566.812139950.83162.786029961.18759.79645
9971.84458.2587710014.6758.6094910036.0863.13976 10047.366.5955810161.05 67.9477
10172.4269.2968310195.0673.7659810216.17 77.184210247.5681.4488410257.5888.06592
10277.6193.3918410297.65  97.278 10327.7104.205910337.72106.068910346.58106.8339
#Mann= 3 , 0 , 0
 9688.84  0.0606       0 9688.84  0.0606       010346.58  0.0606       0
#XS Ineff= 2 , 0
       09897.337                       0
Bank Sta=9688.84,10346.58
Exp/Cntr=0.3,0.1

Type RM Length L Ch R = 1 ,12081.51,238.071600,238.071600,238.071600
XS GIS Cut Line= 6
808223.365119384716940.176263416808238.229062924717145.180971808
808334.355131396717589.396888248808354.725309576717746.064929912
808358.248317763 717914.35216542808342.755404045718075.390670975
#Sta/Elev= 30
9545.448130.15689570.289122.09959590.316110.92769650.396 98.85379680.49889.44052
9700.63586.792349710.704  82.0359750.97873.024519801.70669.413389821.998 76.2517
9832.14375.331089842.28966.32461 9955.0466.139699996.25555.4429610016.8457.31725
10037.4263.6857410160.5767.9054910201.3585.0902410221.6287.3214710292.3789.03797
10352.7373.5981410422.8870.4145210432.8971.89914 10442.984.73549 10462.984.63192
 10472.974.92759 10492.973.1530710603.0779.5229610663.4488.7141110694.1296.96392
#Mann= 3 , 0 , 0
9545.448    0.06       09545.448    0.06       010694.12    0.06       0
#XS Ineff= 2 , 0
       09949.692                       0
Bank Sta=9545.448,10694.12
Exp/Cntr=0.3,0.1

Type RM Length L Ch R = 1 ,11843.44,238.071700,238.071700,238.071700
XS GIS Cut Line= 6
808002.362047859716963.778533197808001.691238809717087.166672337
808009.112698303717177.092433748808037.538309766717351.819699345
808096.782652574717646.194899437808115.900226381717863.322095343
#Sta/Elev= 30
9512.684131.90269553.953124.26099633.975 104.0739694.172 98.5525 9714.2493.99827
9734.358 87.68439744.45481.378599754.55177.554719764.64779.037469774.74467.96647
9805.03366.645599835.48762.803979957.879 62.98169988.58753.581279998.824 53.2361
10009.0553.5483110029.4960.0165510111.2559.2919310131.5763.0184310151.8662.11163
10202.5764.3495410232.8363.26266   1025377.1198410263.0982.1481210303.2887.20882
10353.4887.6995210373.51102.361810393.53107.011310403.54112.271710421.88114.0627
#Mann= 3 , 0 , 0
9512.684  0.0455       09512.684  0.0455       010421.88  0.0455       0
#XS Ineff= 2 , 0
       0                 10156.1       0
Bank Sta=9512.684,10421.88
Exp/Cntr=0.3,0.1

Type RM Length L Ch R = 1 ,11605.37,238.071600,238.071600,238.071600
XS GIS Cut Line= 6
807828.386964322716958.724140216807815.643205451717041.454530105
 807807.52245636717180.336880985807834.870241304717716.808511616
807832.867677229717887.029008145807826.118758583 717977.57755495
#Sta/Elev= 30
9476.211118.34789573.526 91.21159613.66682.966969623.70179.416549653.75177.80837
9683.76370.759549693.76766.988829723.773 65.44659733.77561.004199823.87960.25289
9944.11261.854289964.15160.57888 9984.1952.1567210004.2351.1457710014.2552.64359
10024.2657.3110110034.2858.2428310084.3660.4569810124.4360.1102810144.4658.44353
10204.5170.9385910234.5380.5011810274.5380.6188310294.5375.0948310324.5469.75037
10334.5470.5707510344.5573.8879510364.5673.6805610444.6694.6548710497.41 103.375
#Mann= 3 , 0 , 0
9476.211  0.0561       09476.211  0.0561       010497.41  0.0561       0
#XS Ineff= 2 , 0
       0                10149.73       0
Bank Sta=9476.211,10497.41
Exp/Cntr=0.3,0.1

Type RM Length L Ch R = 1 ,11367.29,238.071600,238.071600,238.071600
XS GIS Cut Line= 6
807706.974327518716887.063655069807639.177045439717057.103462167
807592.757905608717242.390673836807582.015500775717362.494897375
807584.541438919717663.760971973807540.789671701717963.576738559
#Sta/Elev= 30
 9376.83113.65269450.79488.538259467.75377.245979472.46675.101379504.43372.26268
9515.089  70.3829525.74566.841039547.05665.463879578.66258.147619608.61456.58625
9682.45656.254129954.34860.024489964.35759.496429984.37550.7616910004.3949.90634
 10014.450.9151210024.4157.5326410034.4259.8135910124.4558.1063510134.4663.65644
10154.4777.0378210164.4878.7899510184.5278.9092310194.5682.7779310204.5989.34336
 10234.794.4872810264.9196.9930310345.6194.9183910447.26101.456810476.52104.4379
#Mann= 3 , 0 , 0
 9376.83    0.04       0 9376.83    0.04       010476.52    0.04       0
#XS Ineff= 2 , 0
       0                10044.09       0
Bank Sta=9376.83,10476.52
Exp/Cntr=0.3,0.1

Type RM Length L Ch R = 1 ,11129.22,238.071600,238.071600,238.071600
XS GIS Cut Line= 6
807668.505299527716844.545255702807562.607550517 717030.49322005
 807464.37765133717216.497366695807401.422978874717347.609560834
807311.944306847717555.070729843807192.746294675717802.212004366
#Sta/Elev= 30
9302.037 112.7289349.53598.444029360.10192.404879371.60888.189199383.11679.79044
9389.94976.53024 9417.6473.816579440.65665.940099463.67265.304669490.98457.16406
9521.12255.179249617.97255.066939679.44656.59957 9748.0455.85429 9934.3157.94462
 9963.8556.434119988.75649.9094810010.5447.7211910021.44 53.921410032.3363.27593
10054.1175.2651910086.7875.6117210097.6879.8365710119.7479.8447210137.8584.17991
10174.9185.8935810230.0884.8657410300.6365.1177910322.8167.6487110372.1776.40036
#Mann= 3 , 0 , 0
9302.037  0.0706       09302.037  0.0706       010372.17  0.0706       0
#XS Ineff= 2 , 0
       0                               0
Bank Sta=9302.037,10372.17
Exp/Cntr=0.3,0.1

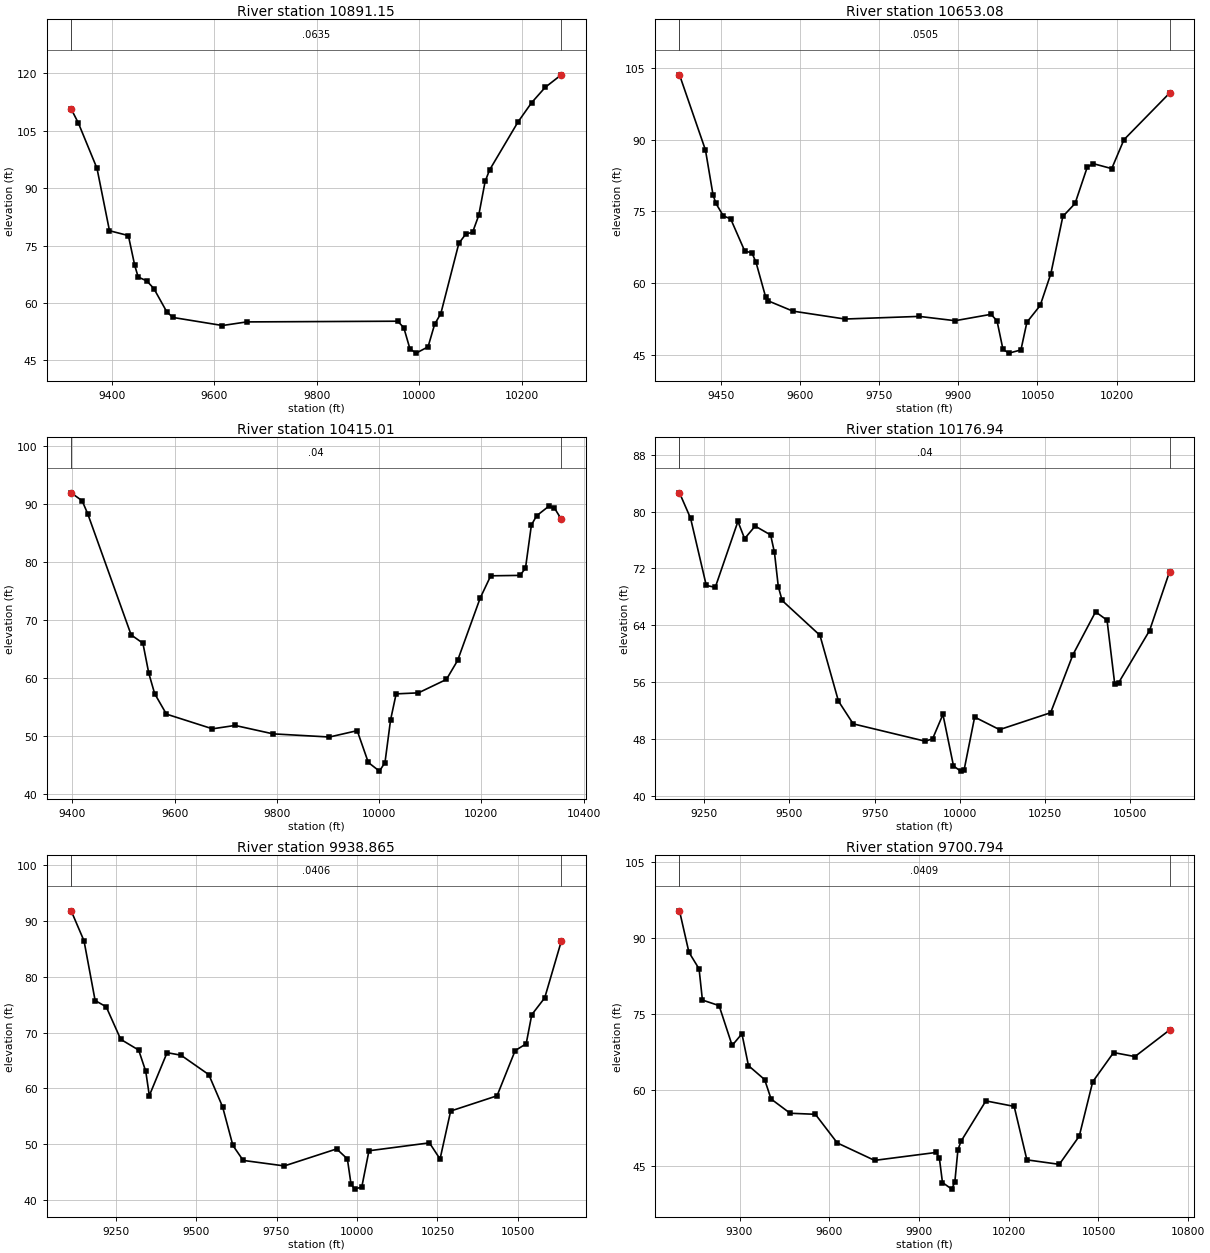
Type RM Length L Ch R = 1 ,10891.15,238.071600,238.071600,238.071600
XS GIS Cut Line= 6
807640.485099509 716813.57556094807500.231216963717007.925859231
807359.157292297717168.283186461807294.949672279717224.571178115
807063.880626033717388.181944938806961.748893636717475.955472944
#Sta/Elev= 30
9320.273110.69899334.181 107.0719370.70195.169339395.04878.871499431.93877.59931
9444.37869.782079451.07566.757329467.88865.750029481.69663.746189506.57557.74283
9518.32856.20067 9615.6154.079599662.98755.024339957.588 55.2079 9969.5953.53448
9981.59347.979159993.59546.8609210016.9848.5026610029.81 54.396310041.9157.20564
10077.11 75.577610090.7978.0245710103.8978.4485210115.8682.8621710128.3991.74793
10137.0694.7496710192.52107.297210219.01112.3276 10245.6116.350310277.03119.6344
#Mann= 3 , 0 , 0
9320.273  0.0635       09320.273  0.0635       010277.03  0.0635       0
#XS Ineff= 2 , 0
       0                               0
Bank Sta=9320.273,10277.03
Exp/Cntr=0.3,0.1

Type RM Length L Ch R = 1 ,10653.08,238.071700,238.071700,238.071700
XS GIS Cut Line= 6
807574.423265638716740.559849804  807469.0825909716840.444878717
807323.347422641716951.078612499807226.387756762 717010.40204437
806977.873968736717143.763290496806801.331989268 717249.57266958
#Sta/Elev= 30
9370.856 103.4939420.13487.810029434.44378.488759439.95876.689979453.939 74.0916
9467.91473.469099494.72266.731399508.12566.405139516.057 64.39659534.23757.20303
 9539.0756.372579585.87754.230929684.81452.581239825.71753.129429893.81252.23084
9961.90753.563859973.25752.206919984.60646.237469995.95545.4722810018.6446.13798
10029.9951.9178110055.1755.4065410075.3962.0295410098.1673.9678110121.3576.67366
10144.5384.2613210156.1384.9677310190.9183.9407810214.0989.9683610300.6899.68626
#Mann= 3 , 0 , 0
9370.856  0.0505       09370.856  0.0505       010300.68  0.0505       0
#XS Ineff= 2 , 0
       0                               0
Bank Sta=9370.856,10300.68
Exp/Cntr=0.3,0.1

Type RM Length L Ch R = 1 ,10415.01,238.071600,238.071600,238.071600
XS GIS Cut Line= 6
807492.559950383 716616.55895764807394.052848154 716682.21011536
807321.155288198716723.582699887 807259.41725168716755.006584183
806790.585790831716958.604029214806633.311831777717037.512243972
#Sta/Elev= 30
9397.60591.995529419.006 90.62689429.86888.407329514.90567.482199537.92966.04344
9549.42760.861749560.92657.338149583.92253.811229673.99451.272649718.16851.85694
9792.42250.40427 9902.8549.858939957.12750.956739978.83845.4679410000.5543.97264
10011.4545.4468210022.3652.7964910033.2657.3037510076.8657.4790610131.6359.79421
10153.5463.0706610197.57 73.8121 10218.3 77.675910275.3877.7486410286.25 78.9647
10297.8786.4477610308.1488.0401210331.5989.65883 10342.989.3767710356.2887.45274
#Mann= 3 , 0 , 0
9397.605    0.04       09397.605    0.04       010356.28    0.04       0
#XS Ineff= 2 , 0
       0                               0
Bank Sta=9397.605,10356.28
Exp/Cntr=0.3,0.1

Type RM Length L Ch R = 1 ,10176.94,238.071600,238.071600,238.071600
XS GIS Cut Line= 6
807631.407261832 716319.96730141807431.643409032 716448.08086985
807265.574342894716530.043558269807066.879844592716606.475744082
806693.932563897716719.750593401806324.364173655716902.960332084
#Sta/Elev= 30
9177.13982.641939209.72679.054929255.75669.600869282.20469.33629 9348.68 78.6095
9368.31676.192799399.204 77.95919444.64476.710199455.91674.239859467.18869.43584
 9478.4667.479839589.47362.576739643.74253.309489687.00650.108129898.488 47.6639
 9920.0347.994829950.42951.43683 9981.4344.1948510002.0943.4518410012.4643.58677
10043.5551.0629210116.6649.2948210266.5551.6756210332.1559.8567510398.5165.88247
10432.1964.7119710454.6555.7696110465.8755.8716910557.05 63.248610615.7871.54451
#Mann= 3 , 0 , 0
9177.139    0.04       09177.139    0.04       010615.78    0.04       0
#XS Ineff= 2 , 0
       0                10163.01       0
Bank Sta=9177.139,10615.78
Exp/Cntr=0.3,0.1

Type RM Length L Ch R = 1 ,9938.865,238.071600,238.071600,238.071600
XS GIS Cut Line= 6
807609.161575581716079.740582655807451.977852494716167.208610893
807340.762082015716219.086071997806842.997431501716415.766956041
806372.106645457716640.744493252806230.959991152716721.738572441
#Sta/Elev= 30
9111.93291.836739151.88186.447139186.34975.750749220.81874.62238 9265.9268.78752
9321.64466.864559343.71363.041879354.74758.691849409.91966.400549453.188 65.9444
9539.52162.46197 9582.4156.68655 9614.3949.760839646.36947.077569774.28846.08691
9936.77249.13557 9970.1247.344189981.31942.877099992.68341.9263210014.8942.31213
10037.2248.8049110225.11 50.225710258.0747.3230810291.0355.9289910435.1758.66297
10491.4566.7733310525.6867.9899110543.0273.2102510583.2376.2234810634.6986.36735
#Mann= 3 , 0 , 0
9111.932  0.0406       09111.932  0.0406       010634.69  0.0406       0
#XS Ineff= 2 , 0
       0                10172.96       0
Bank Sta=9111.932,10634.69
Exp/Cntr=0.3,0.1

Type RM Length L Ch R = 1 ,9700.794,238.071600,238.071600,238.071600
XS GIS Cut Line= 6
807562.711613794715923.668711052807178.546442115716089.645233184
806629.191087465716238.944073648806399.747236667716318.538410307
806262.177419934716385.596432286 806050.27816016716524.820599347
#Sta/Elev= 30
9099.38195.388949130.88987.208569164.84183.921359175.99477.768059231.75976.66883
 9275.3968.803919308.10771.105839329.91964.815179384.08362.055559405.52258.22908
9469.259 55.4128 9553.65 55.20489626.82349.551269751.513 46.10389957.83647.67642
9968.15846.540659978.47941.7322210009.4640.42821 10019.8 41.828110030.1548.19719
10040.4949.8768310123.5857.8531510218.1756.7667510260.6846.2084310369.0345.32271
10435.7850.8973210480.7961.63255 10550.567.40054 10621.866.6036810737.7171.85433
#Mann= 3 , 0 , 0
9099.381  0.0409       09099.381  0.0409       010737.71  0.0409       0
#XS Ineff= 2 , 0
       0                10087.52       0
Bank Sta=9099.381,10737.71
Exp/Cntr=0.3,0.1