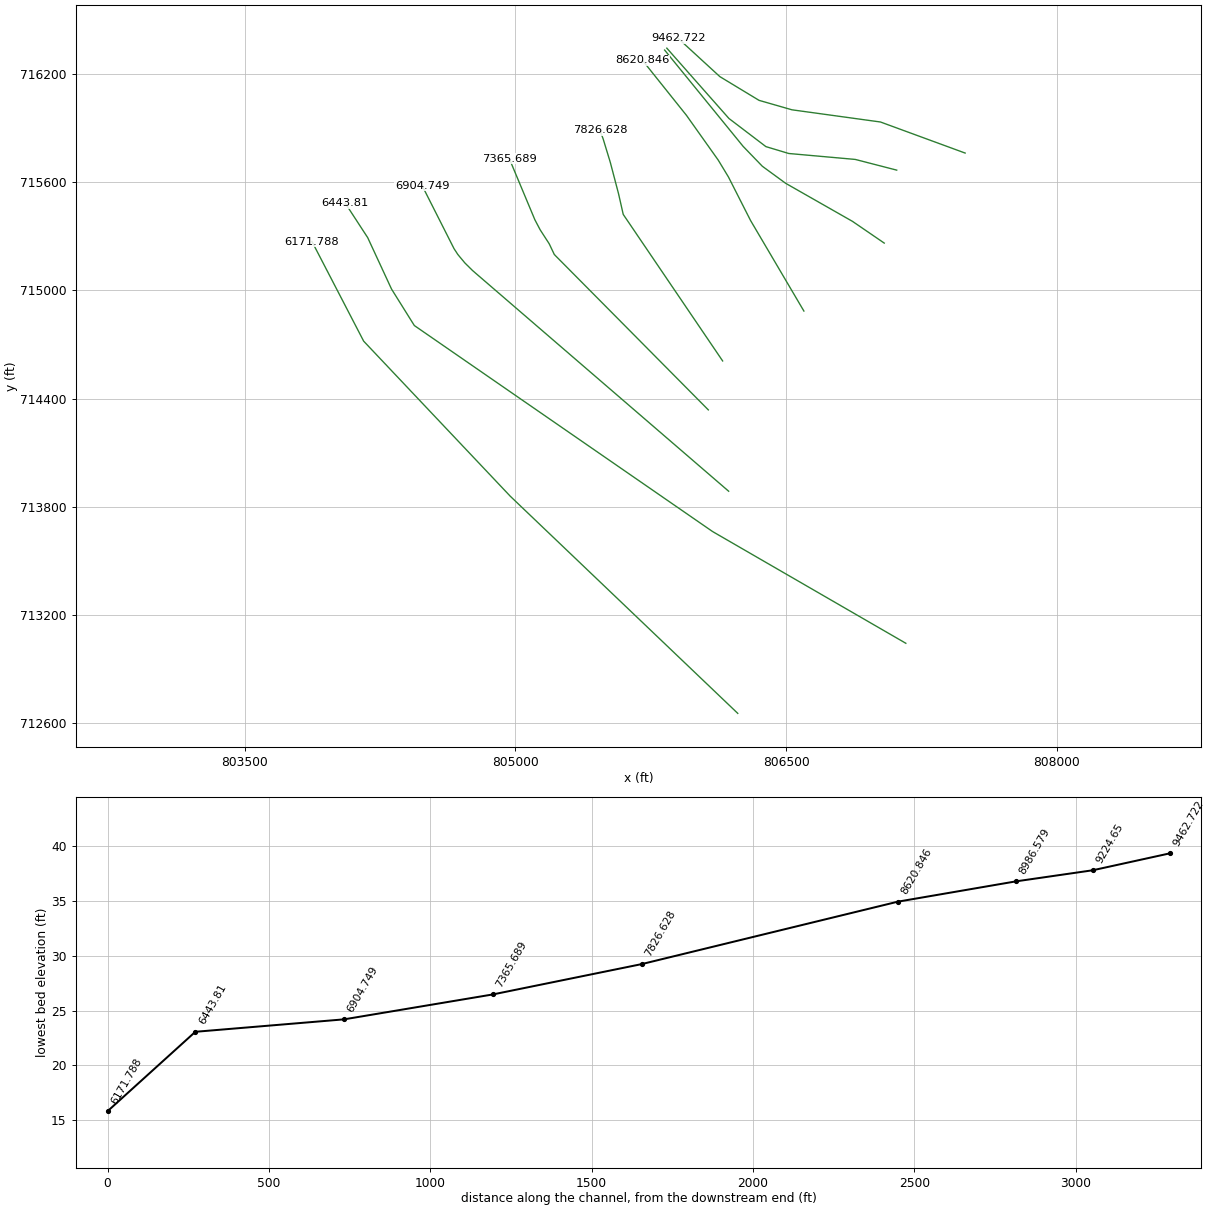
HEC-RAS study 6869_ras.prj: 6869

--- 6869_ras.g01 (geometry) --- (continued)

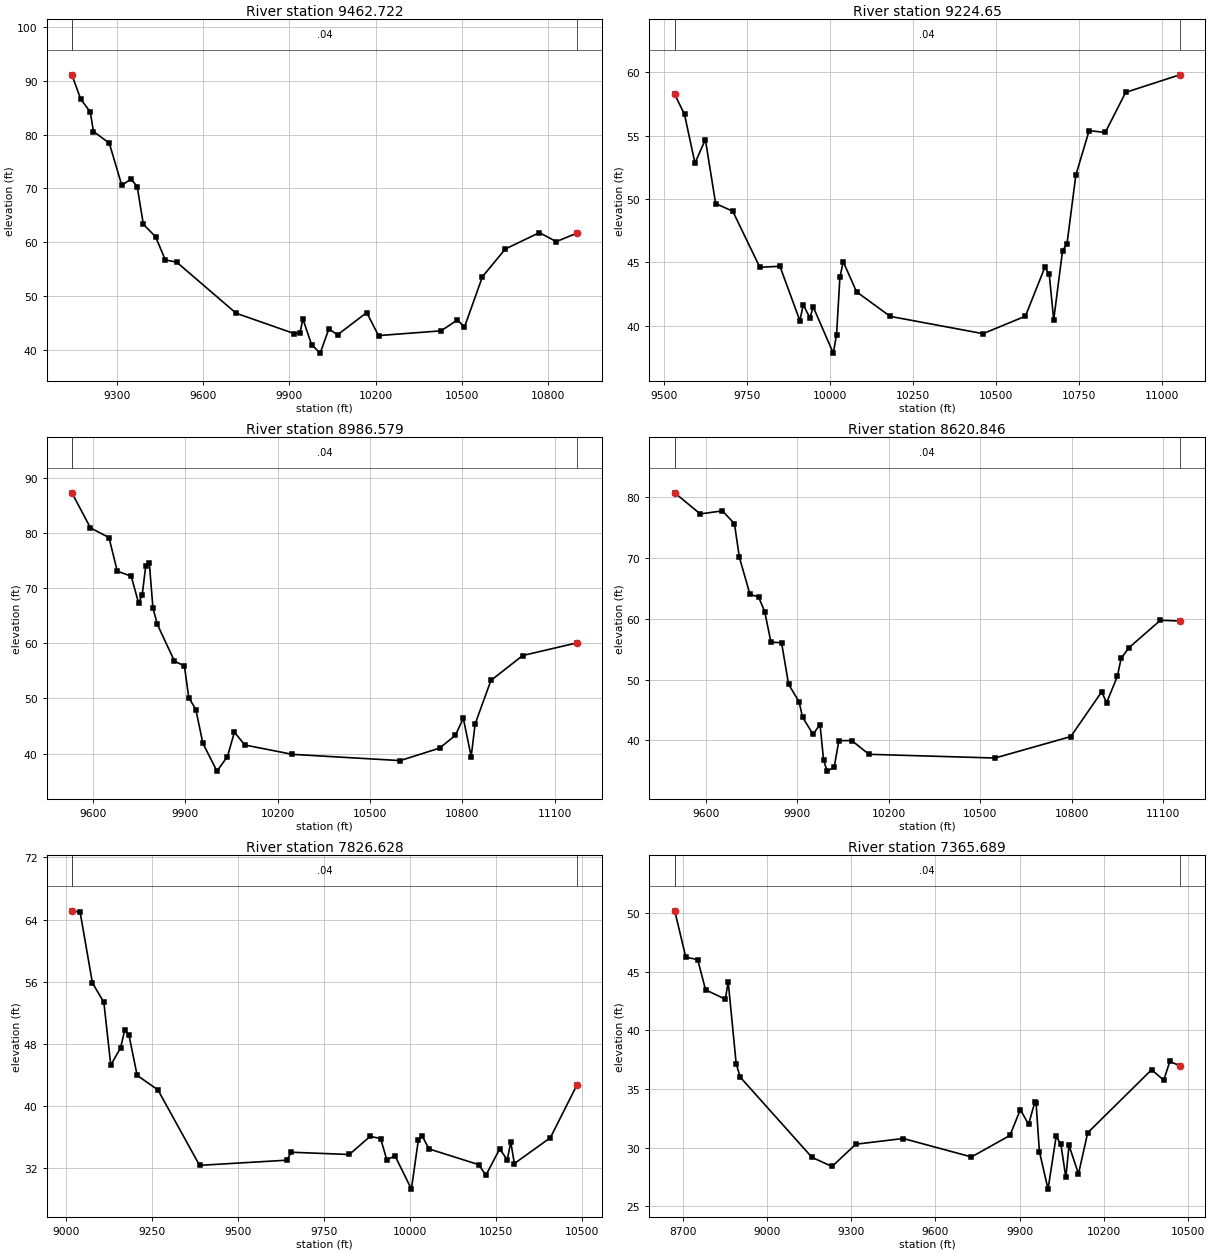
Type RM Length L Ch R = 1 ,9462.722,238.071700,238.071700,238.071700
XS GIS Cut Line= 6
 807492.11862611715760.082616409807023.102206073715932.192081773
806532.336254068715999.812719733806350.104535078716052.180876384
806133.010257231716183.591062526805901.769674504716395.813227958
#Sta/Elev= 30
9144.18791.145469174.58386.647639208.01484.233559219.035 80.59889274.02378.44396
 9317.4670.596789349.69971.746029371.03970.364689392.37963.34613 9435.0661.00826
9468.85356.701199508.54356.282669714.63346.794279916.80643.001919936.885 43.1225
9946.92545.736399977.044 40.952810007.1739.3636710037.3243.8785310067.4742.76735
10168.84 46.913410209.7942.6272810427.3943.5122510484.2745.5464110508.5444.20551
10571.0853.58725 10650.658.7411610769.1661.7845710827.5960.1116610899.4361.68601
#Mann= 3 , 0 , 0
9144.187    0.04       09144.187    0.04       010899.43    0.04       0
#XS Ineff= 2 , 0
       0                10047.72       0
Bank Sta=9144.187,10899.43
Exp/Cntr=0.3,0.1

Type RM Length L Ch R = 1 , 9224.65,238.071600,238.071600,238.071600
XS GIS Cut Line= 6
   807112.951352715665.510983531806883.327995246715724.824858924
806514.745954718715757.736195652806388.053785167715795.865541583
806183.324465556715951.722756274805839.064432718716341.342007817
#Sta/Elev= 30
9533.27658.248689562.68656.669089594.14152.81811 9625.4154.680879656.36949.63173
9707.89949.023249789.20244.602599849.67844.679089909.82440.379599919.84841.63863
9939.89640.608619949.92141.4696710010.0737.8236110020.0939.2850710030.1243.83046
10040.1545.0379710080.2542.6614510181.4740.7241310460.7239.3598710588.0740.74038
10646.4844.59511 10659.844.0416710673.1340.4378210699.7845.9174910713.11 46.4378
10739.7651.8796910779.7455.3891610828.2355.2398310889.6258.40738 11052.2 59.7921
#Mann= 3 , 0 , 0
9533.276    0.04       09533.276    0.04       0 11052.2    0.04       0
#XS Ineff= 2 , 0
       0                10037.76       0
Bank Sta=9533.276,11052.2
Exp/Cntr=0.3,0.1

Type RM Length L Ch R = 1 ,8986.579,365.732200,365.732200,365.732200
XS GIS Cut Line= 6
807043.878691275715261.199838271806868.077992054715381.486851879
 806497.82860691715592.363921918806368.322049898715686.995340876
806262.042504758715797.048431186805826.944998154716330.814014154
#Sta/Elev= 30
 9531.0487.323329591.31380.959019651.49579.208959678.52373.100859723.71372.19806
9747.67667.337289759.35568.721929771.03374.055929782.71274.553159794.39166.39917
9808.96163.424399864.46356.762819896.71555.90339 9910.8950.164859933.78447.99382
9956.67741.8723110002.5336.8091810036.6439.4617410059.2543.8815310093.1641.55226
10247.4839.8554810598.0238.71961 10726.340.9897810777.6143.3113810803.27 46.4151
10828.92 39.446210841.7545.3753810893.0753.2750210996.3757.7933811172.5860.08787
#Mann= 3 , 0 , 0
 9531.04    0.04       0 9531.04    0.04       011172.58    0.04       0
#XS Ineff= 2 , 0
       0                10059.92       0
Bank Sta=9531.04,11172.58
Exp/Cntr=0.3,0.1

Type RM Length L Ch R = 1 ,8620.846,794.218400,794.218400,794.218400
XS GIS Cut Line= 6
806598.597267637 714884.69646131806303.205269838715386.215420257
806180.671362549715627.381352646806124.129638036715720.783943563
805947.318807806715969.916743509805704.209557947716273.911258014
#Sta/Elev= 30
9497.866 80.71059581.474 77.24259654.28477.742539693.80275.632199710.07170.08076
 9744.8564.005499772.864 63.60079793.09661.173489813.54956.152299848.40756.06787
9871.33549.235159905.72646.362529917.18943.83357 9951.5841.00956  9974.642.62013
9986.18436.776139997.76734.9549810020.9535.5747610036.3839.9642710078.6539.97774
10135.0637.7214110548.3737.1086710797.26 40.636310898.5747.9915410914.7646.20311
10949.8850.52808 10962.653.5071810988.0455.2455511091.2159.7557311154.6359.63367
#Mann= 3 , 0 , 0
9497.866    0.04       09497.866    0.04       011154.63    0.04       0
#XS Ineff= 2 , 0
       09890.824        10059.98       0
Bank Sta=9497.866,11154.63
Exp/Cntr=0.3,0.1

Type RM Length L Ch R = 1 ,7826.628,460.939400,460.939400,460.939400
XS GIS Cut Line= 6
806148.370533309714608.204692006805597.542932123715420.185465068
805571.577054411715534.718956858805525.731089473715709.174722016
805486.790147215715836.899528503805468.173675299715887.835216463
#Sta/Elev= 30
9017.81565.123429041.63264.957949077.25855.852539110.61353.317439130.69745.23212
9158.94947.451549171.03349.700049183.11649.178999207.28443.915389267.70342.03834
9388.54232.313339642.30232.980689654.386 34.0056 9823.5633.712669883.97936.04831
9914.46535.768549932.31533.041929956.48233.5197610003.8929.2487310024.2335.64524
10034.4736.1603310055.0434.4286410199.4832.4040510220.1631.0364910260.38 34.4213
 10282.2 33.035710292.5435.3115610302.9432.5465310407.4935.8758110484.6142.66615
#Mann= 3 , 0 , 0
9017.815    0.04       09017.815    0.04       010484.61    0.04       0
#XS Ineff= 2 , 0
       09225.784        10037.22       0
Bank Sta=9017.815,10484.61
Exp/Cntr=0.3,0.1

Type RM Length L Ch R = 1 ,7365.689,460.939500,460.939500,460.939500
XS GIS Cut Line= 6
806069.087529832 714336.97336432805215.775194466715197.867312729
 805187.07917583715257.912696153805137.332243025715334.740646437
805107.858629078 715390.73052673 804966.93528083  715727.6564226
#Sta/Elev= 30
8671.29750.191698710.759 46.23968752.999 46.03918781.159 43.45968851.55942.65824
 8861.7744.13701 8890.1837.168348904.38536.026299160.07729.186669231.71928.41017
9316.19930.305699485.15930.793139728.28129.220799865.31931.056099902.42433.25814
9931.61631.989469953.84933.890029958.39533.78907 9970.2629.67324   10001 26.4795
10029.8730.9676510046.52 30.325810064.4127.4717210075.7130.2058510109.4527.77695
10142.2331.2795410369.78 36.652110413.0535.7609910434.69 37.360510470.0236.99503
#Mann= 3 , 0 , 0
8671.297    0.04       08671.297    0.04       010470.02    0.04       0
#XS Ineff= 2 , 0
       0 9066.95        10044.79       0
Bank Sta=8671.297,10470.02
Exp/Cntr=0.3,0.1

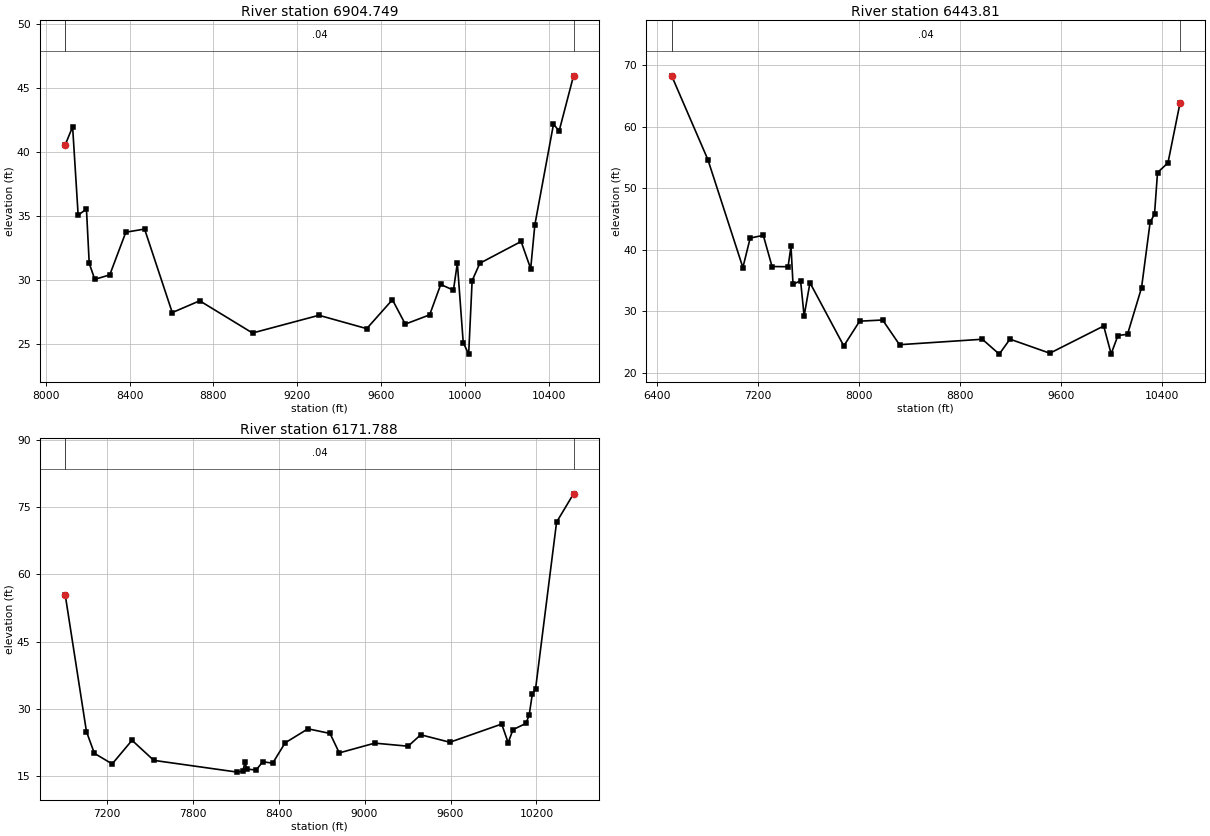
Type RM Length L Ch R = 1 ,6904.749,460.939500,460.939500,460.939500
XS GIS Cut Line= 6
806181.752850563713886.312081396804763.509282827715108.390717372
804720.348194778715151.002943769804681.095787346715198.091221586
804659.791972518715230.795862064804483.209711641715579.734873965
#Sta/Elev= 30
8093.37540.57436 8128.6941.98981 8155.0935.076078194.692 35.55258207.89231.30663
8234.293  30.0558305.83530.401758382.43133.74064  8471.933.988368603.90327.45394
8734.774 28.37558986.714 25.85629303.52427.242579531.37626.198129653.93128.45919
9715.20826.551249831.53927.27659 9884.3429.653459944.99729.206229963.54331.33183
9991.56825.1125610017.6124.2040210034.1129.9525910070.9831.31466 10267.633.01559
10313.3330.8882510333.1634.3151810422.1242.1912910449.1741.66219 10517.745.97474
#Mann= 3 , 0 , 0
8093.375    0.04       08093.375    0.04       0 10517.7    0.04       0
#XS Ineff= 2 , 0
       08844.053        10122.05       0
Bank Sta=8093.375,10517.7
Exp/Cntr=0.3,0.1

Type RM Length L Ch R = 1 , 6443.81,272.022100,272.022100,272.022100
XS GIS Cut Line= 6
807163.498306339713043.788391348806092.636874058713662.913705306
804439.975853831714804.506067887804313.671287596715006.521032929
804181.728104621715291.360859081804056.436607897 715483.65948233
#Sta/Elev= 30
6515.18268.315896802.224 54.68177079.44937.142327137.20441.938357241.16342.37955
7310.46937.308767437.53137.275247460.63340.619327476.59934.407047536.53735.00535
7564.59229.265097610.79634.674087878.97324.397178004.49628.423378186.80328.61308
8320.49524.598718976.80125.485929110.61123.066179195.56925.501739511.56823.21477
9938.23827.639169997.20623.10587 10051.226.0931610126.9526.28606   1023833.84661
10306.3244.5245210340.9245.8189110364.7552.5890810447.46 54.163410542.8663.88601
#Mann= 3 , 0 , 0
6515.182    0.04       06515.182    0.04       010542.86    0.04       0
#XS Ineff= 2 , 0
       08557.815        10035.35       0
Bank Sta=6515.182,10542.86
Exp/Cntr=0.3,0.1

Type RM Length L Ch R = 1 ,6171.788,0.000000,0.000000,0.000000
XS GIS Cut Line= 4
806232.182976586712655.383159193804971.766309919713858.508159193
804159.266309919714717.883159193803872.807976586715269.966492526
#Sta/Elev= 30
 6911.3855.452767059.55424.889137114.85220.015257239.27217.640367377.517  22.928
7529.58618.440238112.895 15.80948151.68716.069668165.51118.057938179.33616.49974
8243.23916.268188289.93118.130598359.10217.813728445.99822.352078605.30925.49275
8759.10524.46176  8823.820.109889071.24922.292489304.14221.60424 9392.1524.16222
9595.25822.488429957.17426.5576610002.2422.3949110036.0425.3057510126.1626.70535
 10148.728.5314210171.2333.3464110193.7634.4823510340.2271.7102310458.4778.03731
#Mann= 3 , 0 , 0
 6911.38    0.04       0 6911.38    0.04       010458.47    0.04       0
#XS Ineff= 2 , 0
       08610.041        10061.23       0
Bank Sta=6911.38,10458.47
Exp/Cntr=0.3,0.1